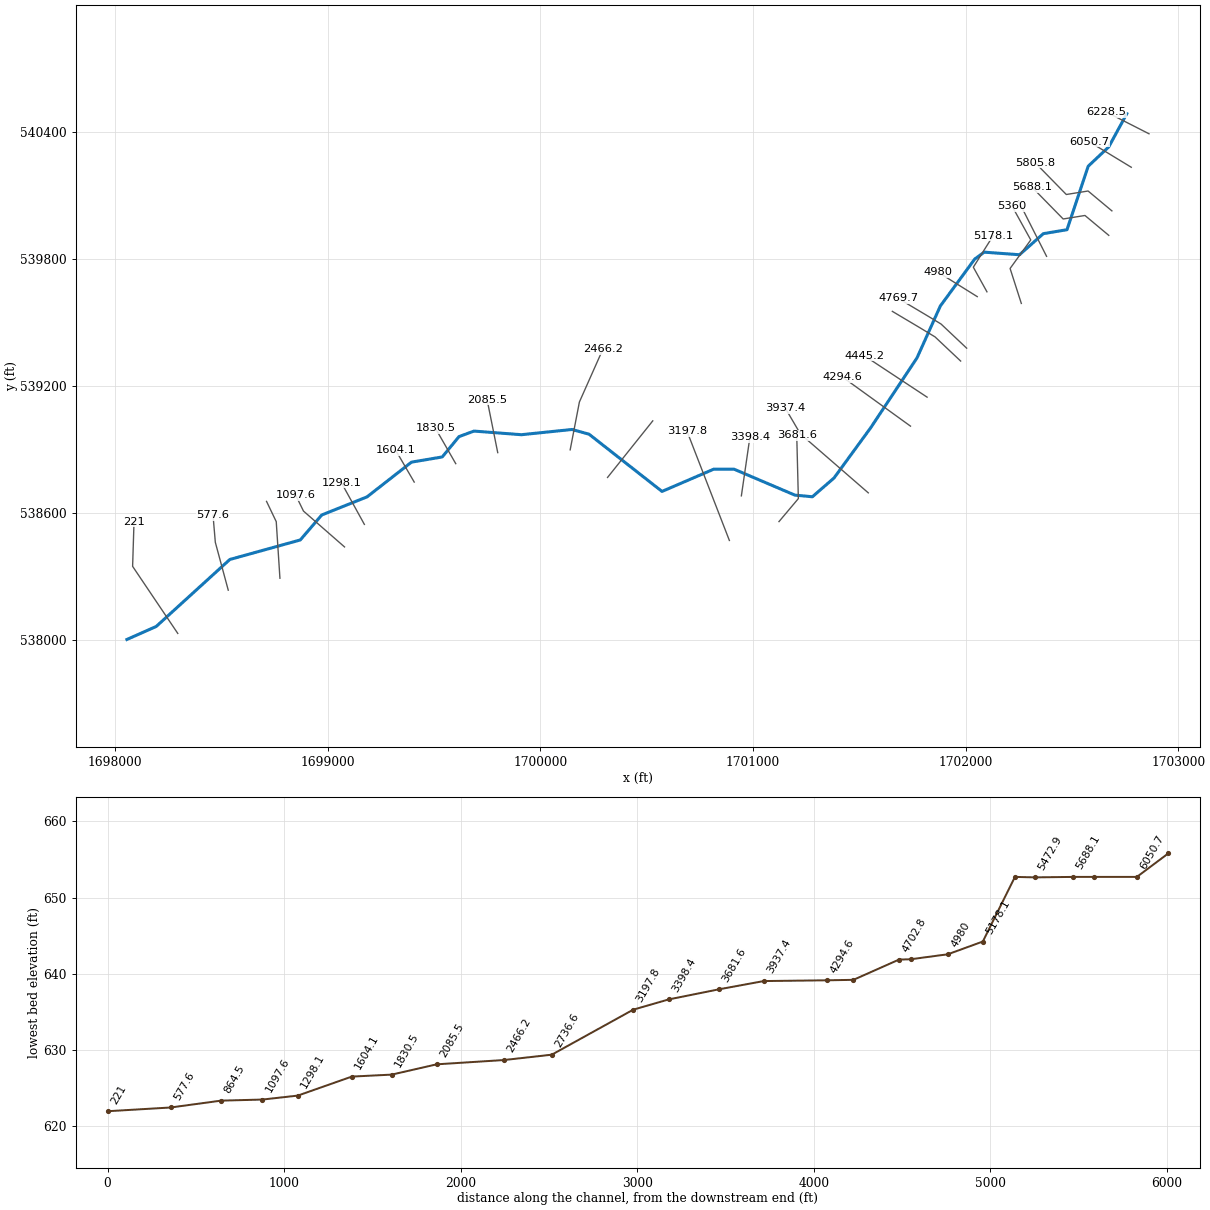
--- LongBr.prj (project) ---

Proj Title=LongBr
Current Plan=p01
Default Exp/Contr=0,0
English Units
Geom File=g01
Flow File=f01
Plan File=p01
BEGIN DESCRIPTION:
AMEC Environment & Infrastructure, 2013
Projection: NAD 1983 State Plane West Virginia South FIPS 4702 (US Feet)
Vertical Datum: NAVD 1988
END DESCRIPTION:
DSS Export Rating Curves= 0
DSS Export Rating Curve Sorted= 0
DSS Export Volume Flow Curves= 0
DXF OffsetX= 0
DXF OffsetY= 0
DXF ScaleX= 0
DXF ScaleY= 0

--- LongBr.p01 (plan) ---

Plan Title=Floodplain
Program Version=4.00
Geom File=g01
Flow File=f01
K Sum by GR=0
Std Step Tol=0.01
Critical Tol=0.01
Num of Std Step Trials=20
Max Error Tol=0.3
Flow Tol Ratio=0.001
Split Flow NTrial=30
Split Flow Tol=0.02
Split Flow Ratio=0.02
Log Output Level=0
Friction Slope Method=1
Unsteady Friction Slope Method=2
Unsteady Bridges Friction Slope Method=1
Global Log Level=0
CheckData=False
Run HTab=0
Run UNet=0
Run PostProcess=0
UNET Theta=0
UNET Theta Warmup=0
UNET ZTol=0
UNET ZSATol=0
UNET MxIter=0
UNET MaxInSteps=0
UNET DtIC=0
UNET DtMin=0
UNET MaxCRTS=0
UNET WFStab=0
UNET SFStab=0
UNET WFX=0
UNET SFX=0
UNET DSS MLevel=0
UNET DZMax Abort=0
UNET Convert EG Bridges=0
UNET Use Existing IB Tables=0
UNET Froude Limit=0
UNET Froude Power=0
Write IC File=0
Echo Input=False
Echo Output=False
Write Detailed=0

--- LongBr.f01 (steady flow) ---

Flow Title=USGS Regress. Eqn. (2010) - Western-Plateaus
Program Version=4.10
Number of Profiles= 1
Profile Names=P100yr
River Rch & RM=LongBr,Main            ,6228.5
     956
River Rch & RM=LongBr,Main            ,2466.2
    1049
River Rch & RM=LongBr,Main            ,1604.1
    1096
River Rch & RM=LongBr,Main            ,864.5
    1112
River Rch & RM=LongBr,Main            ,221
    1116
Boundary for River Rch & Prof#=LongBr,Main            , 1
Up Type= 0
Dn Type= 3
Dn Slope=0.00133
DSS Import GetInterval= 0
DSS Import GetPeak= 0
DSS Import FillOption= 0

--- LongBr.g01 (geometry) ---

Geom Title=USGS 3m DEM
Program Version=4.10

River Reach=LongBr          ,Main
Reach XY= 30
     1702758.177      540484.516     1702673.204      540327.754
     1702576.614      540236.578     1702476.782      539937.015
     1702365.426      539918.274     1702253.425      539818.762
     1702087.377      539831.039      1702042.76      539798.528
     1701881.057      539577.106      1701771.25        539332.2
     1701553.334      539002.457     1701380.742      538765.319
      1701279.02      538676.802     1701196.568      538684.656
     1700910.359      538807.002     1700814.873      538807.002
     1700571.689      538702.017     1700228.464      538972.041
     1700148.435      538994.338     1699910.201      538969.632
     1699687.281      538986.743     1699616.751      538960.701
      1699537.93      538864.676     1699393.227      538840.259
     1699184.132      538676.325     1698971.053      538590.816
     1698870.035       538472.99     1698538.616      538380.854
     1698192.363      538064.787     1698054.425      538003.473

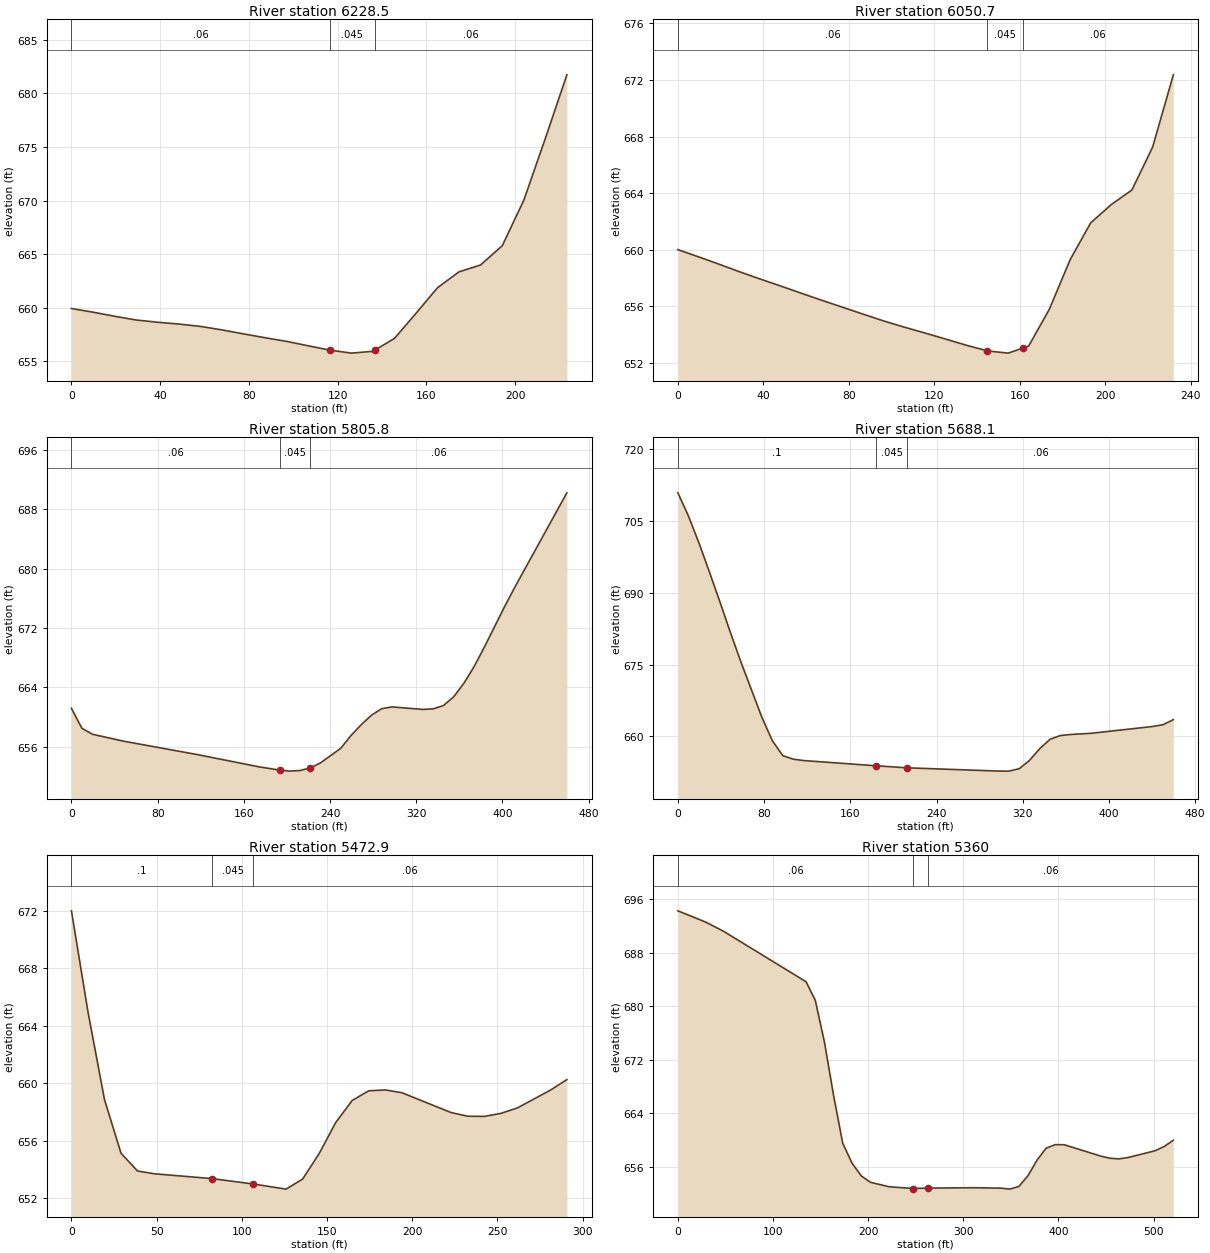
Type RM Length L Ch R = 1 ,6228.5  ,199.9,177.8,204.9
XS GIS Cut Line= 2
     1702862.485      540389.631     1702663.642      540491.207
#Sta/Elev= 26
       0  659.94     9.7   659.6    19.4  659.22    29.1  658.87    38.8  658.66
    48.5  658.49    58.2  658.27      68  657.94    77.7  657.57    87.4  657.21
    97.1  656.87   106.8  656.46   116.5  656.06   121.7  655.91   126.2  655.78
   135.9  655.95   136.7  656.05   145.6  657.15   155.3  659.49     165  661.88
   174.7  663.36   184.4     664   194.2   665.8   203.9  670.04   213.6   675.8
   223.3  681.73
#Mann= 3 , 0 , 0
       0     .06       0   116.5    .045       0   136.7     .06       0
Bank Sta=116.5,136.7
XS Rating Curve= 0 ,0
Exp/Cntr=0.3,0.1

Type RM Length L Ch R = 1 ,6050.7  ,228.7,244.9,265.5
XS GIS Cut Line= 2
     1702779.141      540231.599     1702581.165      540352.276
#Sta/Elev= 27
       0  660.01     9.7   659.5    19.3  658.98      29  658.44    38.6  657.93
    48.3  657.43      58  656.92    67.6  656.42    77.3  655.93      87  655.44
    96.6  654.96   106.3  654.52   115.9  654.11   125.6  653.68   135.2  653.25
   144.9  652.86   146.5  652.83   154.6   652.7   161.5  653.06   164.2   653.2
   173.9  655.81   183.6   659.3   193.2   661.9   202.9   663.2   212.5  664.22
   222.2  667.25   231.9  672.36
#Mann= 3 , 0 , 0
       0     .06       0   144.9    .045       0   161.5     .06       0
Bank Sta=144.9,161.5
XS Rating Curve= 0 ,0
Exp/Cntr=0.3,0.1

Type RM Length L Ch R = 1 ,5805.8  ,117.9,117.7,117.5
XS GIS Cut Line= 4
     1702687.985       540025.81     1702575.971      540119.577
     1702473.515      540103.073     1702326.766      540253.276
#Sta/Elev= 27
       0  661.17     9.7  658.48    19.5  657.67    48.7  656.73   116.9  654.93
   174.4  653.27   193.2  652.84   202.7   652.7   212.1  652.78   221.6  653.13
     231   653.8   249.9  655.77   259.4  657.49     269  658.97   278.5  660.25
     288  661.12   297.6  661.36   326.2  661.02   335.8   661.1   345.3  661.55
   354.8  662.73   364.4  664.58   373.9  666.84   383.5   669.5   402.6  675.05
   412.1  677.66   459.8  690.23
#Mann= 3 , 0 , 0
       0     .06       0   193.2    .045       0   221.6     .06       0
Bank Sta=193.2,221.6
XS Rating Curve= 0 ,0
Exp/Cntr=0.3,0.1

Type RM Length L Ch R = 1 ,5688.1  ,246.5,215.2,184.5
XS GIS Cut Line= 4
     1702673.232      539910.328     1702561.217      540004.095
     1702458.762      539987.591     1702312.012      540137.793
#Sta/Elev= 26
       0  710.91     9.7   706.1    19.5  700.46    29.2  694.38      39   688.1
    48.7  681.72    58.4  675.58    77.9  663.99    87.6  659.08    97.4  655.93
   107.1   655.2   116.9  654.91   183.8  653.82   212.9  653.39   297.6  652.71
   307.1   652.7   316.7   653.2   326.2  654.92   335.8  657.39   345.3  659.35
   354.8  660.14   364.4  660.36   383.5  660.61   440.8  662.04   450.3  662.41
   459.8  663.47
#Mann= 3 , 0 , 0
       0      .1       0   183.8    .045       0   212.9     .06       0
Bank Sta=183.8,212.9
XS Rating Curve= 0 ,0
Exp/Cntr=0.3,0.1

Type RM Length L Ch R = 1 ,5472.9  ,143,112.9,73.8
XS GIS Cut Line= 2
     1702380.628      539811.325     1702249.501      540070.932
#Sta/Elev= 23
       0     672     9.7  664.98    19.4  658.87    29.1  655.14    38.8   653.9
    48.5  653.71    82.6  653.37   106.6     653     126  652.64   135.7  653.34
   145.4  655.11   155.1  657.27   164.8  658.81   174.5  659.48   184.2  659.54
   193.9  659.35     223  657.96   232.7  657.71   242.4   657.7   252.1  657.91
   261.8  658.29   281.2  659.53   290.8  660.26
#Mann= 3 , 0 , 0
       0      .1       0    82.6    .045       0   106.6     .06       0
Bank Sta=82.6,106.6
XS Rating Curve= 0 ,0
Exp/Cntr=0.3,0.1

Type RM Length L Ch R = 1 ,5360    ,229.6,181.9,194.9
XS GIS Cut Line= 4
     1702261.922      539589.061     1702209.103      539754.051
     1702306.322      539888.648     1702218.667      540047.532
#Sta/Elev= 30
       0  694.22    28.9  692.56    48.1  691.16   134.7  683.64   144.4  680.87
     154  674.65   163.6   666.7   173.2  659.57     183  656.58   192.8  654.66
   202.5  653.71   222.1  653.05   247.5  652.79   262.5  652.85     310  652.91
   339.3  652.85   348.8   652.7   358.4   653.1   367.9   654.7   377.5  657.04
     387   658.8   396.6  659.34   406.1  659.32   444.3  657.63   453.9  657.31
   463.4  657.21     473  657.41   501.6  658.43   511.2  659.07   520.7  659.99
#Mann= 3 , 0 , 0
       0     .06       0   247.5    .045       0   262.5     .06       0
Bank Sta=247.5,262.5
XS Rating Curve= 0 ,0
Exp/Cntr=0.3,0.1

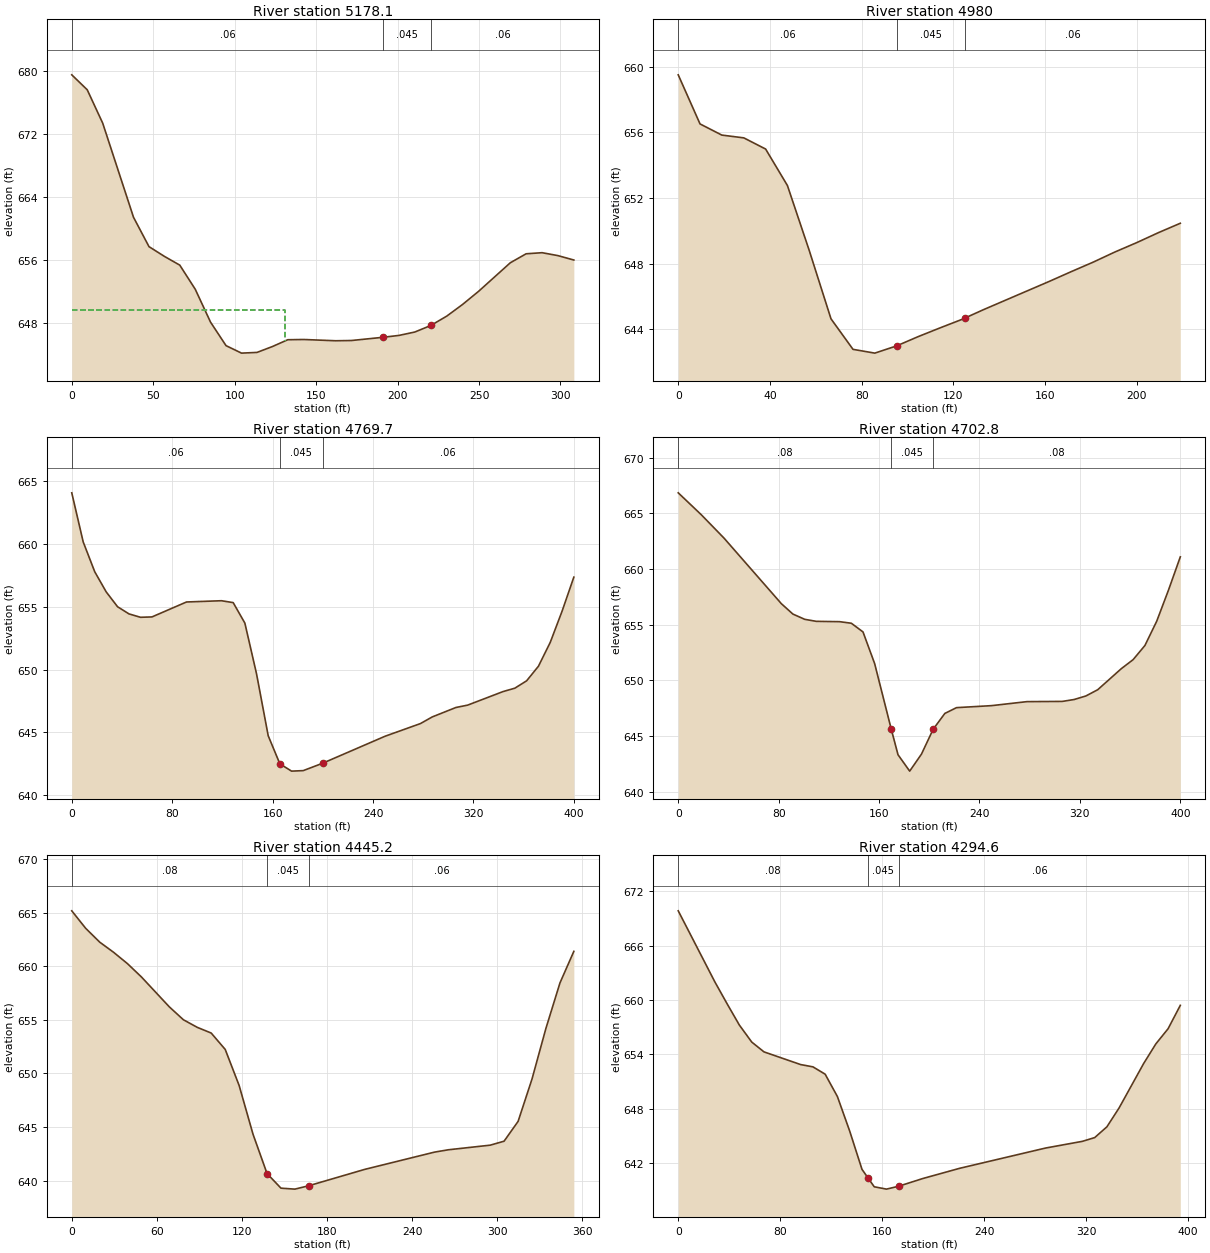
Type RM Length L Ch R = 1 ,5178.1  ,106.9,198.1,237.2
XS GIS Cut Line= 3
     1702100.185      539643.946     1702036.142      539760.074
     1702129.472      539908.773
#Sta/Elev= 29
       0  679.56     9.5  677.66      19  673.42    37.9  661.48    47.4  657.75
    56.8  656.52    66.3   655.4    75.8  652.34    85.2  648.16    94.7  645.18
   104.2  644.23   113.7  644.32   123.1  645.06   132.6  645.93   142.4  645.96
   161.9   645.8   171.6  645.83   191.1  646.24   200.9  646.48   210.6  646.91
   220.4  647.74   230.2  648.93   239.9  650.41   249.7  652.07   269.2   655.7
   278.9  656.84   288.7  656.98   298.4  656.61   308.2  656.05
#Mann= 3 , 0 , 0
       0     .06       0   191.1    .045       0   220.4     .06       0
#XS Ineff= 2 , 0
          131.13  649.67
Permanent Ineff=
       F       F
Bank Sta=191.1,220.4
XS Rating Curve= 0 ,0
Exp/Cntr=0.3,0.1

Type RM Length L Ch R = 1 ,4980    ,209.5,210.2,210.3
XS GIS Cut Line= 2
     1702054.602       539621.15     1701868.999       539737.27
#Sta/Elev= 26
       0  659.51     9.5  656.52      19  655.84    28.6  655.67    38.1  654.99
    47.6  652.77    57.1  648.82    66.6  644.65    76.2  642.79    85.7  642.56
    95.2     643   104.7  643.57   109.9  643.86   114.2   644.1   123.8  644.62
   124.9  644.69   133.3  645.22   142.8  645.79   152.3  646.36   161.8  646.93
   171.3  647.52   180.9   648.1   190.4  648.72   199.9  649.29   209.4   649.9
   218.9  650.47
#Mann= 3 , 0 , 0
       0     .06       0    95.2    .045       0   124.9     .06       0
Bank Sta=95.2,124.9
XS Rating Curve= 0 ,0
Exp/Cntr=0.3,0.1

Type RM Length L Ch R = 1 ,4769.7  ,66.6,66.9,67
XS GIS Cut Line= 5
     1702004.692      539378.029     1701944.994      539434.463
      1701884.21      539491.982     1701812.575      539535.392
     1701683.413      539612.443
#Sta/Elev= 30
       0  664.09     9.1  660.18    18.3   657.8    27.4   656.2    36.5  655.01
    45.6  654.44    54.8  654.17    63.9   654.2    91.4  655.39   119.3  655.49
   128.6  655.34   137.9  653.71   147.2  649.67   156.5  644.73   165.8  642.49
   175.1  641.91   184.4  641.95   199.9  642.54   249.6  644.69   277.8   645.7
   287.2  646.23     306  646.98   315.4  647.17   343.6  648.25     353  648.52
   362.4  649.11   371.8  650.27   381.2  652.17   390.6  654.65     400  657.37
#Mann= 3 , 0 , 0
       0     .06       0   165.8    .045       0   199.9     .06       0
Bank Sta=165.8,199.9
XS Rating Curve= 0 ,0
Exp/Cntr=0.3,0.1

Type RM Length L Ch R = 1 ,4702.8  ,258.5,257.6,256.7
XS GIS Cut Line= 5
     1701976.477      539317.247     1701916.779      539373.682
     1701855.995      539431.201     1701784.359       539474.61
     1701655.198      539551.662
#Sta/Elev= 30
       0  666.85    18.3  664.89    36.5  662.78    82.2  656.89    91.4  655.96
   100.8  655.49     110  655.31   128.6  655.28   137.9  655.14   147.2  654.36
   156.5  651.51  169.58645.6864   175.1  643.33   184.4  641.86   193.8  643.39
   203.1  645.62   212.4  647.04   221.7  647.56   249.6  647.74   277.8   648.1
     306  648.12   315.4  648.29   324.8  648.61   334.2  649.17     353  651.06
   362.4  651.87   371.8  653.14   381.2  655.32   390.6  658.12     400   661.1
#Mann= 3 , 0 , 0
       0     .08       0  169.58    .045       0   203.1     .08       0
Bank Sta=169.58,203.1
XS Rating Curve= 0 ,0
Exp/Cntr=0.3,0.1

Type RM Length L Ch R = 1 ,4445.2  ,151.6,150.6,149.7
XS GIS Cut Line= 2
     1701818.671      539146.848     1701523.443      539342.191
#Sta/Elev= 27
       0  665.17     9.8  663.54    19.7  662.25    29.5   661.3    39.3  660.24
    49.2  658.99    68.8  656.21    78.7  655.01    88.5   654.3    98.3  653.77
   108.2  652.24     118  648.88   127.8  644.33   137.7  640.66   147.5   639.3
   157.3  639.21   167.2  639.53   206.5  641.05   255.7  642.66   265.5  642.88
     295  643.31   304.8  643.68   314.7  645.53   324.5  649.48   334.3   654.2
   344.2  658.44     354  661.39
#Mann= 3 , 0 , 0
       0     .08       0   137.7    .045       0   167.2     .06       0
Bank Sta=137.7,167.2
XS Rating Curve= 0 ,0
Exp/Cntr=0.3,0.1

Type RM Length L Ch R = 1 ,4294.6  ,359.2,357.2,355.1
XS GIS Cut Line= 2
     1701740.535      539010.089     1701421.427      539241.247
#Sta/Elev= 27
       0  669.83    28.8  661.98    38.4  659.57      48  657.23    57.7  655.36
    67.3  654.28    96.1  652.88   105.7  652.63   115.3  651.82   124.9  649.36
   134.6  645.53   144.2  641.33   148.9  640.39   153.8  639.41   163.4  639.15
     173  639.47   192.2  640.33     221  641.45   288.3  643.68   317.2  644.42
   326.8  644.83   336.4  646.02     346  648.11   365.2  652.99   374.8  655.16
   384.4  656.83     394  659.41
#Mann= 3 , 0 , 0
       0     .08       0   148.9    .045       0     173     .06       0
Bank Sta=148.9,173
XS Rating Curve= 0 ,0
Exp/Cntr=0.3,0.1

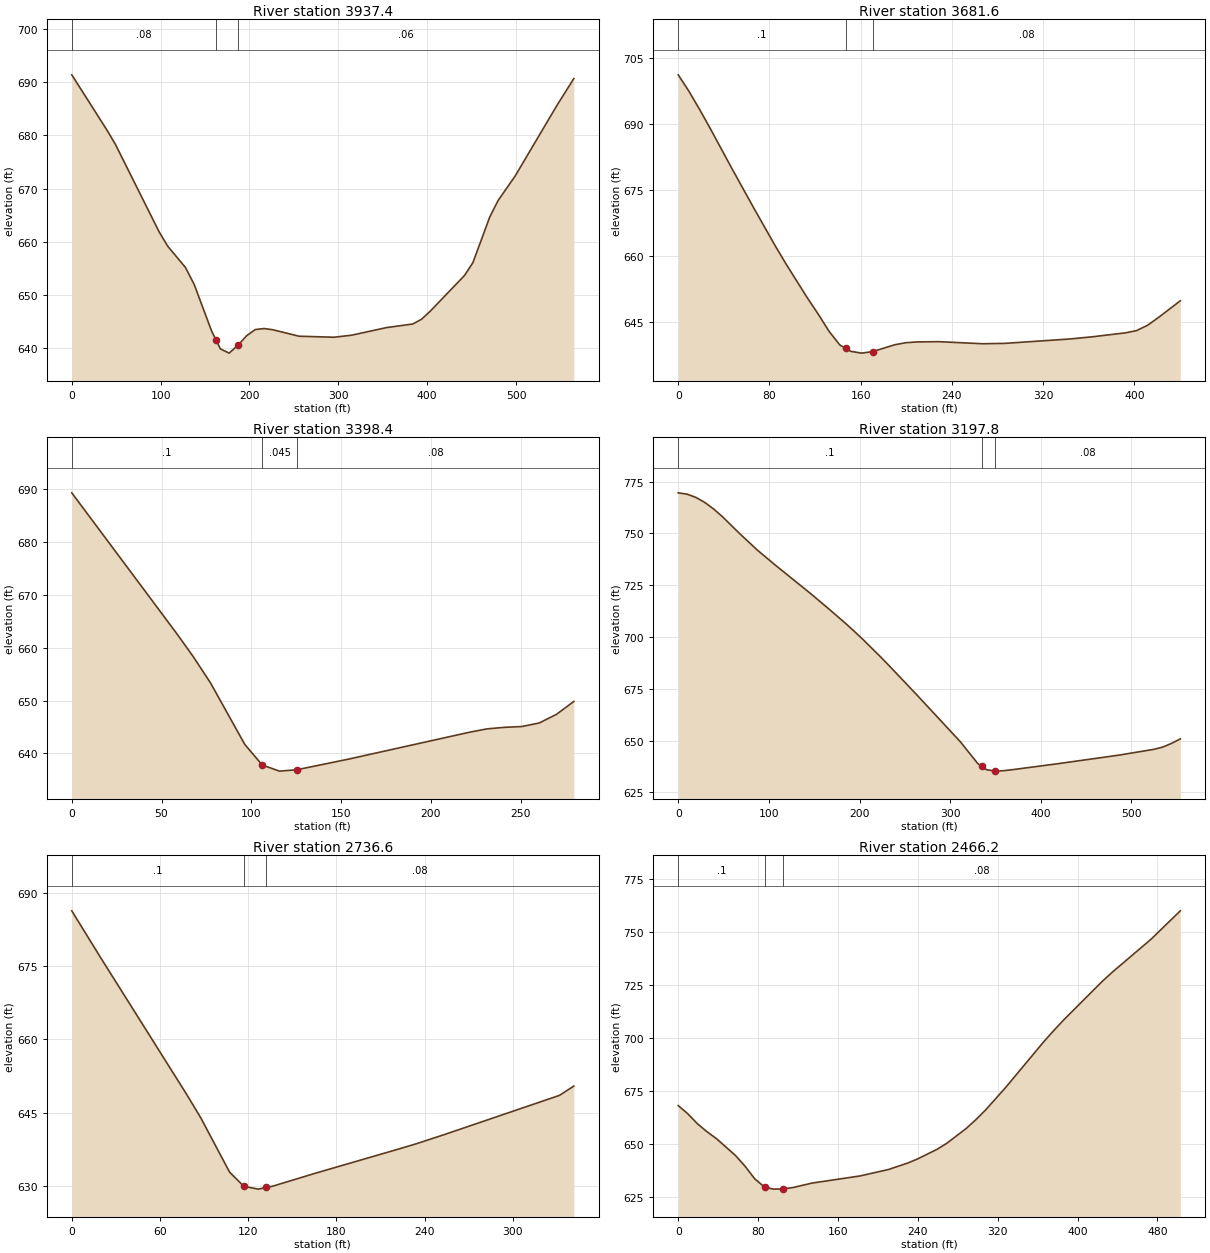
Type RM Length L Ch R = 1 ,3937.4  ,282.4,255.9,236.5
XS GIS Cut Line= 3
     1701541.936      538695.325     1701222.826      538973.153
     1701151.185      539095.793
#Sta/Elev= 30
       0   691.4    39.4  681.06    49.2   678.3    98.4  661.84   108.2  659.12
   127.9  655.18   137.8  651.97   157.4   643.2   162.5  641.47   167.3  639.84
   177.1  639.05     187  640.52   196.8  642.32   206.6  643.49   216.5  643.67
   226.3  643.45   255.8  642.23   295.2  642.04   314.9  642.42   354.2  643.85
   383.8  644.53   393.6  645.41   403.4  646.93     442  653.65   451.5  656.07
   470.4  664.63   479.9  667.77   498.9  672.33   546.2  685.68   565.1   690.7
#Mann= 3 , 0 , 0
       0     .08       0   162.5    .045       0     187     .06       0
Bank Sta=162.5,187
XS Rating Curve= 0 ,0
Exp/Cntr=0.3,0.1

Type RM Length L Ch R = 1 ,3681.6  ,278.7,283.2,278.6
XS GIS Cut Line= 3
     1701121.916      538559.629     1701213.078       538668.17
     1701205.461       538966.64
#Sta/Elev= 29
       0  701.11     9.4  697.38    18.9  693.18    28.4  688.78    47.2  679.79
    66.2  670.91      85  662.34    94.5  658.21   113.4  650.43   122.8   646.8
   132.3   642.9   141.7  639.81   146.8  639.05   151.4  638.36     161  637.96
   170.6  638.32   189.9  639.86   199.5  640.32   209.2   640.5   228.4  640.56
     267  640.09   286.2  640.17     344  641.18   363.3  641.67   392.2  642.56
   401.8  643.06   411.4  644.25     421  646.02   440.3  649.84
#Mann= 3 , 0 , 0
       0      .1       0   146.8    .045       0   170.6     .08       0
Bank Sta=146.8,170.6
XS Rating Curve= 0 ,0
Exp/Cntr=0.3,0.1

Type RM Length L Ch R = 1 ,3398.4  ,188.9,200.5,212.2
XS GIS Cut Line= 2
     1700944.996      538681.176     1700985.136      538957.943
#Sta/Elev= 16
       0  689.31    57.9  662.94    67.5  658.39    77.2  653.39    96.4  641.69
   106.1   637.8   115.7  636.64   125.4   636.9   154.3  638.92   221.8  644.02
   231.4  644.64   241.1  644.93   250.7  645.08   260.4  645.75     270  647.38
   279.7  649.83
#Mann= 3 , 0 , 0
       0      .1       0   106.1    .045       0   125.4     .08       0
Bank Sta=106.1,125.4
XS Rating Curve= 0 ,0
Exp/Cntr=0.3,0.1

Type RM Length L Ch R = 1 ,3197.8  ,485,461.2,436.9
XS GIS Cut Line= 2
     1700888.572      538470.615     1700688.834      538987.228
#Sta/Elev= 30
       0  769.58     9.7  768.95    19.4  767.38    29.2  764.98    38.9  761.84
    48.6  758.14      68  749.82    87.4   741.9   106.9  734.78   145.8  721.05
   165.2  713.92   184.6  706.58   194.3  702.74   204.1  698.69   223.5  690.31
   233.2  685.93   262.4  672.48     311  649.59   330.4     639  335.06637.5583
   340.1     636   349.8   635.3   359.5  635.53   369.2  636.03   417.8  638.82
   485.9     643   524.7  645.82   534.4  646.88   544.2  648.69   553.9  650.86
#Mann= 3 , 0 , 0
       0      .1       0  335.06    .045       0   349.8     .08       0
Bank Sta=335.06,349.8
XS Rating Curve= 0 ,0
Exp/Cntr=0.3,0.1

Type RM Length L Ch R = 1 ,2736.6  ,259.1,270.5,280.9
XS GIS Cut Line= 2
     1700315.488      538767.963     1700528.199      539034.972
#Sta/Elev= 15
       0  686.26    19.5  676.76      78  648.82    87.8  643.93   107.3  632.88
     117  629.97   126.8   629.4   132.4  629.74   136.6     630   165.8  632.66
   224.3  637.77   234.1  638.65   253.6  640.57   331.6  648.55   341.4  650.46
#Mann= 3 , 0 , 0
       0      .1       0     117    .045       0   132.4     .08       0
Bank Sta=117,132.4
XS Rating Curve= 0 ,0
Exp/Cntr=0.3,0.1

Type RM Length L Ch R = 1 ,2466.2  ,371.2,380.7,389.4
XS GIS Cut Line= 3
     1700139.654      538898.193     1700183.053      539123.948
     1700293.741      539373.585
#Sta/Elev= 30
       0  668.07     9.6  664.23    19.2  659.52    28.7  655.81    38.3  652.49
    57.5  644.49      67  639.48    76.6  633.58    86.8  629.52    95.8   628.7
   105.4   628.8   114.9  629.45   134.1  631.55     182   634.9   210.7  637.96
   229.9  640.99   239.6  642.89   259.2  647.43   268.9  650.26   288.4  657.25
   298.2  661.43   307.9  666.01   327.4  676.27   366.4  698.28   376.2  703.44
   385.9  708.32   424.9  726.66   434.7  730.89   473.7  746.49     503  759.87
#Mann= 3 , 0 , 0
       0      .1       0    86.8    .045       0   105.4     .08       0
Bank Sta=86.8,105.4
XS Rating Curve= 0 ,0
Exp/Cntr=0.3,0.1

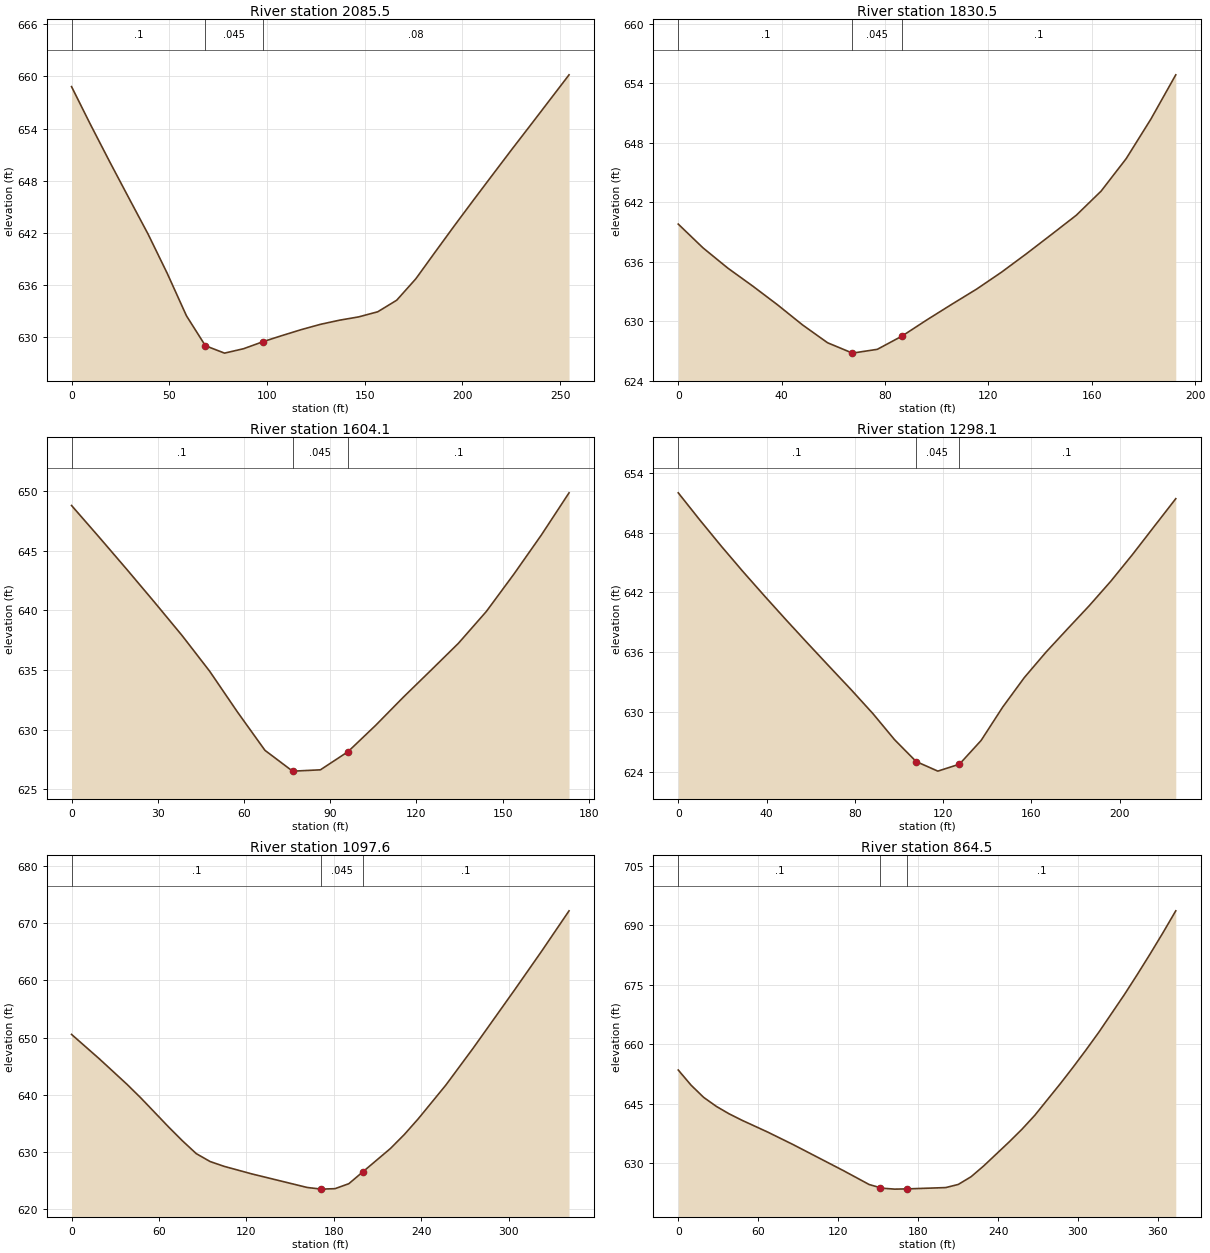
Type RM Length L Ch R = 1 ,2085.5  ,246.6,255,262
XS GIS Cut Line= 2
     1699798.855      538885.146     1699748.913      539134.773
#Sta/Elev= 29
       0  658.82     9.8  654.41    19.6  650.14    29.4  645.97    39.2  641.83
      49  637.31    58.8  632.44    68.5  628.99    78.3  628.14    88.1  628.65
    88.8  628.71    97.9  629.45   103.8  629.88   107.7  630.16   117.5  630.84
   127.3  631.45   137.1  631.93   146.9  632.31   156.7   632.9   166.4  634.23
   176.2   636.7     186  639.75   195.8  642.77   205.6  645.73   215.4  648.65
   225.2  651.56     235  654.42   244.8   657.3   254.6  660.18
#Mann= 3 , 0 , 0
       0      .1       0    68.5    .045       0    97.9     .08       0
Bank Sta=68.5,97.9
XS Rating Curve= 0 ,0
Exp/Cntr=0.3,0.1

Type RM Length L Ch R = 1 ,1830.5  ,226.1,226.4,226.6
XS GIS Cut Line= 2
     1699601.325      538833.037     1699505.804      539000.174
#Sta/Elev= 23
       0  639.79     9.6  637.39    19.2  635.35    28.9  633.53    38.5  631.64
    48.1  629.63    57.8  627.83    61.7  627.41    67.4  626.79    76.7  627.16
      77  627.17    86.6  628.51    96.2  630.14   105.9  631.72   115.5  633.25
   125.1  634.95   134.8  636.82   144.4  638.74     154  640.68   163.6  643.11
   173.3  646.38   182.9  650.38   192.5  654.83
#Mann= 3 , 0 , 0
       0      .1       0    67.4    .045       0    86.6      .1       0
Bank Sta=67.4,86.6
XS Rating Curve= 0 ,0
Exp/Cntr=0.3,0.1

Type RM Length L Ch R = 1 ,1604.1  ,306.1,305.9,305
XS GIS Cut Line= 2
     1699405.969      538746.196     1699319.131      538895.968
#Sta/Elev= 21
       0  648.77     9.6  646.12    19.2  643.43    28.8  640.69    38.5  637.87
    48.1  634.88    57.7  631.49    67.3  628.27    76.9  626.53      79  626.55
    86.6  626.64      94  627.81    96.2  628.16   105.8  630.36   115.4  632.71
     125  634.96   134.6  637.23   144.3  639.89   153.9  643.02   163.5  646.31
   173.1  649.83
#Mann= 3 , 0 , 0
       0      .1       0    76.9    .045       0    96.2      .1       0
Bank Sta=76.9,96.2
XS Rating Curve= 0 ,0
Exp/Cntr=0.3,0.1

Type RM Length L Ch R = 1 ,1298.1  ,192.3,200.5,208.4
XS GIS Cut Line= 2
     1699171.547      538546.477     1699062.999      538744.003
#Sta/Elev= 26
       0  652.02     9.8  649.28    19.6  646.63    29.4  644.08    39.2  641.62
      49  639.21    58.8  636.85    68.6  634.52    78.4  632.21    88.2  629.82
      98   627.2   107.8     625     112  624.59   117.6  624.04     127  624.71
   127.4  624.74   137.2  627.12     147  630.48   156.8  633.45   166.6     636
   176.4  638.35   186.2  640.67     196  643.14   205.8  645.82   215.6  648.63
   225.4  651.43
#Mann= 3 , 0 , 0
       0      .1       0   107.8    .045       0     127      .1       0
Bank Sta=107.8,127
XS Rating Curve= 0 ,0
Exp/Cntr=0.3,0.1

Type RM Length L Ch R = 1 ,1097.6  ,251.3,233.2,215.1
XS GIS Cut Line= 3
     1699078.214      538440.106     1698885.011      538609.408
     1698848.104       538685.38
#Sta/Elev= 23
       0  650.55      19   646.3    38.1  641.82    47.6  639.44    66.6  634.38
    76.1  631.96    85.6  629.72    95.1  628.34   104.7   627.5   123.7  626.18
   161.7  623.81   171.3  623.52   180.8   623.6   190.3  624.47   199.8  626.52
   218.8  630.61   228.3  633.04   237.9   635.8   256.9  641.71   275.7  648.18
   303.8  658.24   322.6  665.09   341.4  672.14
#Mann= 3 , 0 , 0
       0      .1       0   171.3    .045       0   199.8      .1       0
Bank Sta=171.3,199.8
XS Rating Curve= 0 ,0
Exp/Cntr=0.3,0.1

Type RM Length L Ch R = 1 ,864.5   ,282.6,286.9,291.1
XS GIS Cut Line= 3
     1698774.327      538292.479     1698756.944      538559.473
     1698711.353      538654.981
#Sta/Elev= 30
       0  653.47     9.6  649.65    19.1  646.55    28.7  644.26    38.2   642.4
    47.8  640.78    66.9  637.83      86  634.67   124.2  628.01   143.3  624.54
   151.6  623.74   152.9  623.62   162.4  623.38     172  623.44   200.7  623.77
   210.2  624.57   219.8  626.52   229.3  629.26   248.4  635.32     258  638.52
   267.6  642.03   286.8  650.04   296.4  654.21     306  658.53   315.7  663.04
   334.9  672.56   344.5  677.59   354.2  682.82   363.8  688.16   373.4  693.69
#Mann= 3 , 0 , 0
       0      .1       0   151.6    .045       0     172      .1       0
Bank Sta=151.6,172
XS Rating Curve= 0 ,0
Exp/Cntr=0.3,0.1

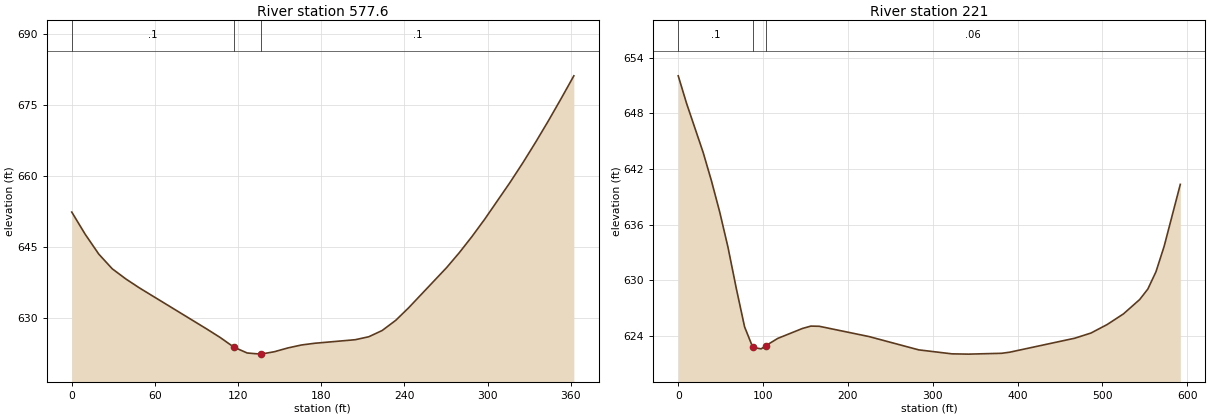
Type RM Length L Ch R = 1 ,577.6   ,348.8,356.6,364.3
XS GIS Cut Line= 3
     1698531.213      538236.025     1698470.419      538461.773
     1698459.557      538589.843
#Sta/Elev= 30
       0  652.42     9.7  647.74    19.5  643.56    29.2  640.47      39  638.33
    48.7  636.46    97.4  627.78   107.2  625.97   116.9  623.96   126.6  622.72
   136.4  622.48   146.1  622.98   155.9  623.78   165.6   624.4   175.3  624.77
   204.6  625.52   214.3  626.14     224  627.46   233.8  629.61     243  632.22
   270.5  640.72   279.7  643.88   288.9  647.31   298.1  650.97   316.4  658.73
   325.6  662.85   334.8  667.18     344  671.69   353.1  676.33   362.3  681.14
#Mann= 3 , 0 , 0
       0      .1       0   116.9    .045       0   136.4      .1       0
Bank Sta=116.9,136.4
XS Rating Curve= 0 ,0
Exp/Cntr=0.3,0.1

Type RM Length L Ch R = 1 ,221     ,224.9,221,215.2
XS GIS Cut Line= 3
     1698293.753      538031.965      1698081.32      538348.485
     1698087.943      538558.984
#Sta/Elev= 30
       0  652.07     9.8   649.1    29.3  643.81    39.1  640.74    48.9  637.35
    58.6  633.56    68.4  629.11    78.2  624.94    87.9  622.72    97.7  622.56
   102.9  622.88   117.3  623.69   146.6  624.77   156.4  625.02   166.2     625
   224.8  623.89   283.5  622.45   322.6  622.02   342.1  621.99   381.2  622.08
   390.8   622.2   467.4  623.71   486.5  624.27   505.6  625.19   524.8  626.34
   543.9  627.89   553.5  629.02   563.1  630.89   572.7  633.63   591.8  640.34
#Mann= 3 , 0 , 0
       0      .1       0    87.9    .045       0   102.9     .06       0
Bank Sta=87.9,102.9
XS Rating Curve= 0 ,0
Exp/Cntr=0.3,0.1

Chan Stop Cuts=-1
Use User Specified Reach Order=0
Composite Channel Slope=5